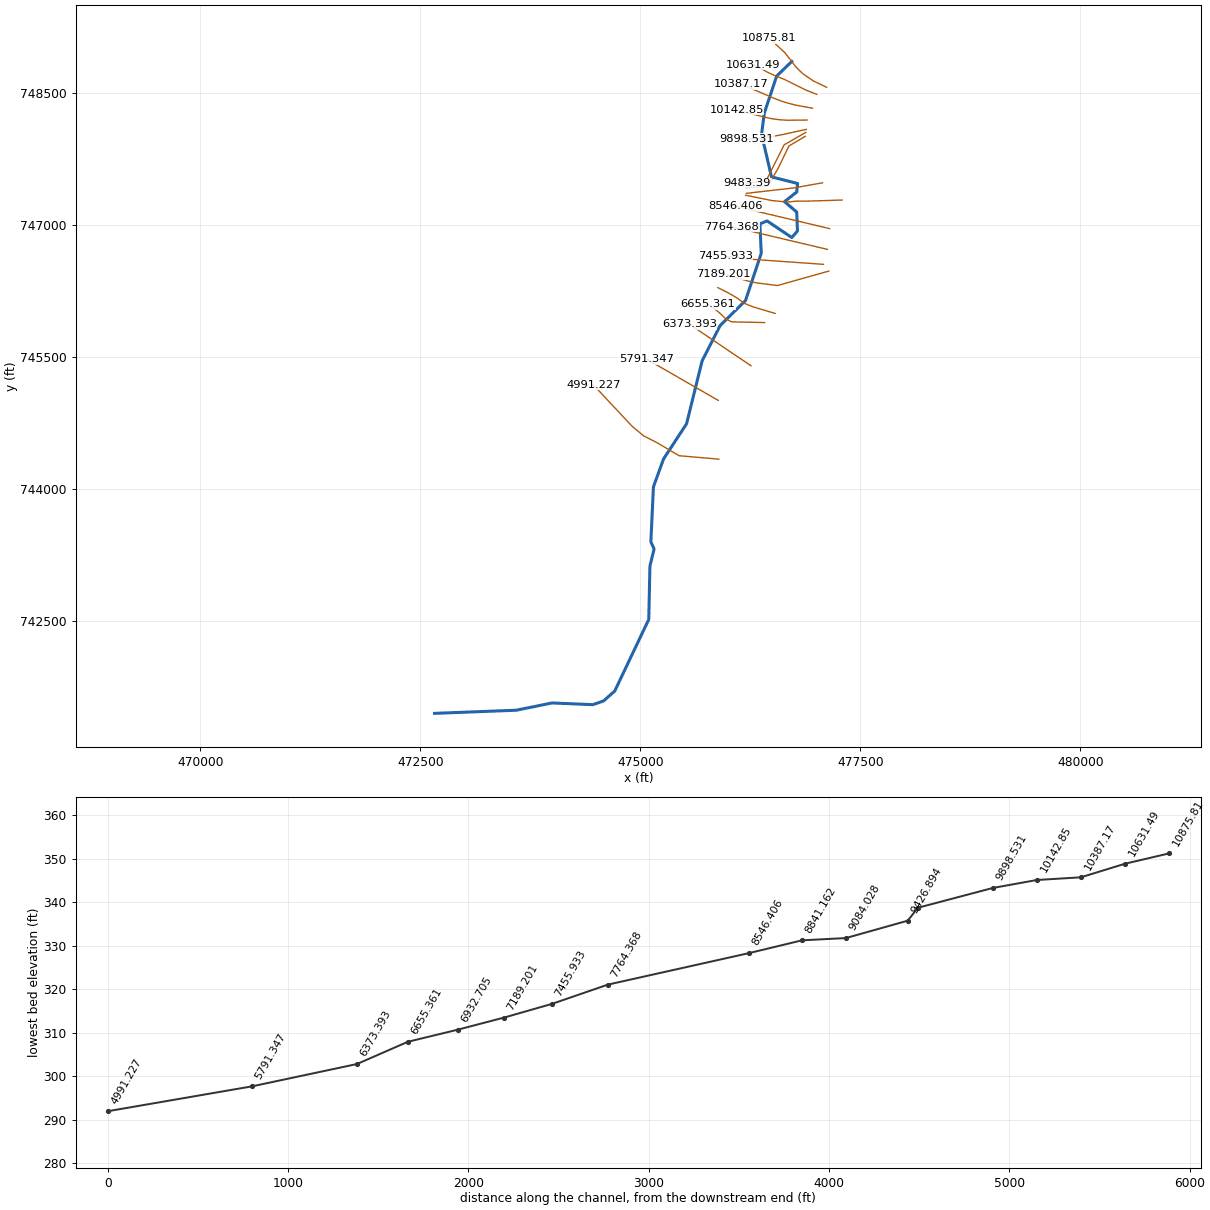
--- 2527_ras.prj (project) ---

Proj Title=2527
Current Plan=p01
Default Exp/Contr=0.3,0.1
English Units
Geom File=g01
Flow File=f01
Plan File=p01
Y Axis Title=Elevation
X Axis Title(PF)=Main Channel Distance
X Axis Title(XS)=Station
BEGIN DESCRIPTION:
RFD model 2527 exported to HEC-RAS
END DESCRIPTION:

--- 2527_ras.p01 (plan) ---

Plan Title=Plan 01
Program Version=4.10
Short Identifier=Plan 01
Geom File=g01
Flow File=f01
Subcritical Flow
Calc Critical at every XS
Secant Critical Depth

--- 2527_ras.f01 (steady flow) ---

Flow Title=Flow 01
Program Version=5.01
Number of Profiles= 6
Profile Names=10yr,25yr,50yr,100yr,100plus,500yr
River Rch & RM=2527,18,10875.81
  834.04 1478.58 2137.29 2807.54 4099.01 6287.55
River Rch & RM=2527,18,10631.49
  836.36 1482.94 2143.82  2816.4 4111.95 6305.95
River Rch & RM=2527,18,10387.17
  872.62 1550.22 2243.99 2951.31 4308.92  6580.7
River Rch & RM=2527,18,10142.85
  886.17 1575.61 2282.03 3002.83 4384.13 6686.47
River Rch & RM=2527,18,9898.531
  887.54 1578.19  2285.9 3008.07 4391.78 6697.25
River Rch & RM=2527,18, 9483.39
  904.13 1609.35 2332.64 3071.43 4484.29 6827.27
River Rch & RM=2527,18,9084.028
  933.93 1665.31 2416.59 3185.22 4650.42 7059.83
River Rch & RM=2527,18,8841.162
  934.22 1665.86 2417.42 3186.35 4652.08 7062.17
River Rch & RM=2527,18,8546.406
  940.01 1676.86 2434.03 3209.02 4685.17 7109.02
River Rch & RM=2527,18,7764.368
  947.94 1691.93 2456.81  3240.1 4730.54 7173.24
River Rch & RM=2527,18,7455.933
  950.96 1697.67  2465.5 3251.95 4747.84 7197.69
River Rch & RM=2527,18,7189.201
  952.97  1701.5 2471.28 3259.84 4759.37 7213.98
River Rch & RM=2527,18,6932.705
   955.7 1706.68 2479.12 3270.54 4774.98 7236.07
River Rch & RM=2527,18,6655.361
  958.41 1711.85 2486.94 3281.21 4790.57 7258.12
River Rch & RM=2527,18,6373.393
  959.24 1713.46 2489.37 3284.56 4795.45 7265.08
Boundary for River Rch & Prof#=2527,18,1
Up Type= 0
Dn Type= 2
Boundary for River Rch & Prof#=2527,18,2
Up Type= 0
Dn Type= 2
Boundary for River Rch & Prof#=2527,18,2
Up Type= 0
Dn Type= 2
Boundary for River Rch & Prof#=2527,18,2
Up Type= 0
Dn Type= 2
Boundary for River Rch & Prof#=2527,18,2
Up Type= 0
Dn Type= 2
Boundary for River Rch & Prof#=2527,18,2
Up Type= 0
Dn Type= 2

--- 2527_ras.g01 (geometry) ---

Geom Title=2527
Program Version=4.10

River Reach=2527,18
Reach XY= 30
476722.755657375748861.959896192476550.880657375748695.293229535
476410.255657375 748275.15434064476379.005657494748033.834896192
476491.852879703747549.459896207476788.727879584747474.807118416
476778.311212927747377.584896207476639.422324151747268.209896207
476778.311212927 747150.15434064476786.991768539746934.876562878
476722.755657375746860.223785102476441.505657375747049.459896207
476359.908435136747014.737673968476375.533435136 746681.40434064
476196.713990718746144.946007326475908.868229479745861.196707875
475703.558714956745459.434512496475526.648789495744743.774597466
475265.031293333744343.923705205 475150.10073784744027.257038489
475120.919601232743401.795829535475157.725419372743321.934688613
475110.170182317743124.409816295 475097.21011278742520.763983011
474710.522521645741706.966187328474583.569396645741594.118965089
474460.956549406741551.801256761473997.631896645741571.332506806
473592.900993854741488.867229015472663.229864472741452.889066809

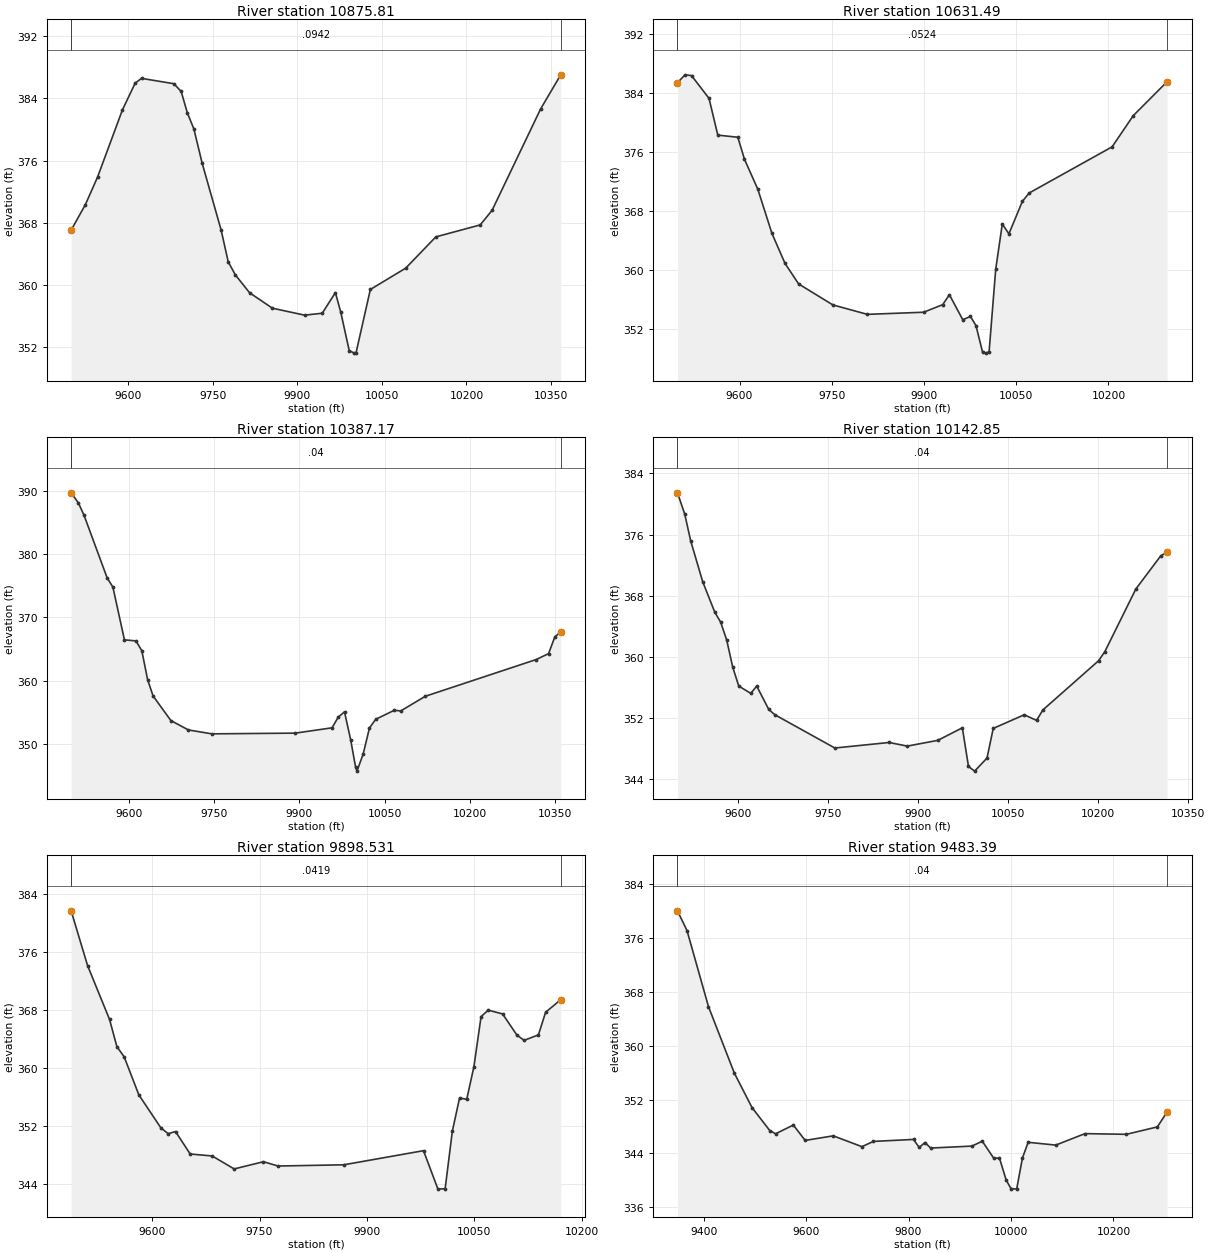
Type RM Length L Ch R = 1 ,10875.81,244.319700,244.319700,244.319700
XS GIS Cut Line= 6
477118.054380864748567.333527893476965.147390366748641.530385166
476847.019078314 748723.04391554476770.239320368748797.740960509
 476643.83850494748961.328999013476467.348387539749124.121190056
#Sta/Elev= 30
9499.095367.03149524.184370.29339545.948373.8652 9590.05382.52379612.536385.9637
9623.899386.58929681.226385.89739694.197384.90699704.961382.18289716.828 380.047
9731.337375.67399765.076367.03659777.648 362.943 9790.22361.26849815.544358.9566
9855.945356.96929913.077356.07129944.389 356.3199967.705358.97999977.276356.4301
 9992.18351.5138   10001 351.17810004.36351.233710029.69359.381210092.33362.1257
10145.78366.158210224.55367.703310245.63 369.59210331.56382.639310367.26387.0435
#Mann= 3 , 0 , 0
9499.095  0.0942       09499.095  0.0942       010367.26  0.0942       0
#XS Ineff= 2 , 0
       09787.145                       0
Bank Sta=9499.095,10367.26
Exp/Cntr=0.3,0.1

Type RM Length L Ch R = 1 ,10631.49,244.319800,244.319800,244.319800
XS GIS Cut Line= 6
477006.455909401748487.273726568 476879.07338801748537.884426385
476639.710633487748656.836759984476516.060350567748706.805083469
476456.391609371 748734.09909524 476287.30681622748826.564373851
#Sta/Elev= 30
9499.046385.34579511.254386.41729521.911386.31269550.323383.23739564.622378.2713
9597.171377.9804 9608.02 375.0019629.719 370.9519652.674364.98359673.902360.9367
9696.061358.15419751.761355.31969807.825354.04449899.396354.33059930.367 355.355
9941.257356.69949963.037353.31699975.533353.76319984.502352.52159995.214348.9334
   10001348.803910005.84348.992310016.57360.118110027.29366.249210038.04364.9257
10060.03369.327210071.03 370.447 10205.9376.686410240.29380.902510295.23385.4824
#Mann= 3 , 0 , 0
9499.046  0.0524       09499.046  0.0524       010295.23  0.0524       0
#XS Ineff= 2 , 0
       09737.798                       0
Bank Sta=9499.046,10295.23
Exp/Cntr=0.3,0.1

Type RM Length L Ch R = 1 ,10387.17,244.319700,244.319700,244.319700
XS GIS Cut Line= 6
476957.431739748748329.988779798476760.747128278748366.426198155
476668.777638078748390.450543121476594.818804234748414.078627169
476526.489069849748440.434736624476145.426421404748603.592809036
#Sta/Elev= 30
 9499.05389.69079511.646388.11859521.777386.12889562.305376.24359572.437374.7852
9592.701366.44859613.071366.27429623.285364.72529633.499360.13279643.042357.5833
9674.356353.68269705.069352.20299746.411351.58299893.068351.69679957.649352.5384
9968.605354.22789979.561355.06269990.517 350.591    9999346.348610001.53345.6894
10012.49348.422810023.45352.513910034.41353.8858 10067.3355.317910078.27355.1982
10121.69357.526510316.61363.334310338.31364.2688 10349.2366.899910359.63367.6967
#Mann= 3 , 0 , 0
 9499.05    0.04       0 9499.05    0.04       010359.63    0.04       0
#XS Ineff= 2 , 0
       09752.608                       0
Bank Sta=9499.05,10359.63
Exp/Cntr=0.3,0.1

Type RM Length L Ch R = 1 ,10142.85,244.319700,244.319700,244.319700
XS GIS Cut Line= 6
476897.024420172748195.622597218476669.733155072748193.243967786
476583.507577807748198.915029362476493.683618456748211.027963787
476398.372832805748231.746147886476094.946442038748311.419390202
#Sta/Elev= 30
9499.062  381.479511.091378.70549521.094375.18199541.101369.83919561.108365.8777
9571.111364.53539581.115362.19549591.118358.66829601.122356.19689621.128355.2412
9631.132356.18989651.135353.13599661.136352.44889761.217348.09129851.676348.8124
9881.948 348.3419932.784349.0912 9973.68350.73229983.904345.67219994.172345.0666
10014.81346.782310025.13350.654210076.76352.435710097.42351.702510107.74353.0624
10200.68359.5085   10211360.6846 10262.8368.897510304.29373.233510314.72373.6926
#Mann= 3 , 0 , 0
9499.062    0.04       09499.062    0.04       010314.72    0.04       0
#XS Ineff= 2 , 0
       0 9734.88                       0
Bank Sta=9499.062,10314.72
Exp/Cntr=0.3,0.1

Type RM Length L Ch R = 1 ,9898.531,415.141100,415.141100,415.141100
XS GIS Cut Line= 6
476887.381887328748089.548677997476629.256240806748032.770215841
476438.676137916747997.143494357476355.713946307747986.741966077
476273.344864983747981.515815364 476213.84747568747981.614900355
#Sta/Elev= 30
9486.858381.63059509.775374.08599540.492366.64929550.731362.9018 9560.97361.4763
9581.448356.23759612.165351.69489622.405350.88649632.644351.18239653.122348.0854
9683.839347.81249714.556346.02429755.498347.01679775.911346.42519867.632346.5926
9979.042348.54259999.223343.237710009.28343.296110019.34351.227410029.39355.8049
10039.42355.629210049.44360.117410059.46367.038610069.48367.929210089.52367.4074
10109.56364.483610119.56 363.76310139.56 364.51210149.56367.626310170.71369.3793
#Mann= 3 , 0 , 0
9486.858  0.0419       09486.858  0.0419       010170.71  0.0419       0
#XS Ineff= 2 , 0
       09765.471        10074.12       0
Bank Sta=9486.858,10170.71
Exp/Cntr=0.3,0.1

Type RM Length L Ch R = 1 , 9483.39,56.495800,56.495800,56.495800
XS GIS Cut Line= 4
476881.156041589 748055.14867827476636.364374903 747914.52367827
476431.552006241747506.805082199 476216.27422845747477.291193318
#Sta/Elev= 30
9348.886380.05059367.518377.11099409.411365.81259459.779355.95689494.377350.8137
9528.975347.40029540.508346.91469575.106348.21689598.171345.92619653.044346.6084
9708.998344.99769731.379345.78019809.715346.07479820.906344.88259832.097345.6114
9843.288344.79449923.842 345.0849944.005 345.8129966.387343.28289977.577343.2954
9990.674340.03259999.959 338.77710011.15 338.68810022.34343.288810033.53345.6486
10087.47345.231810144.55346.937610225.29346.833810285.86 347.93810304.76 350.143
#Mann= 3 , 0 , 0
9348.886    0.04       09348.886    0.04       010304.76    0.04       0
#XS Ineff= 2 , 0
       09677.087        10040.17       0
Bank Sta=9348.886,10304.76
Exp/Cntr=0.3,0.1

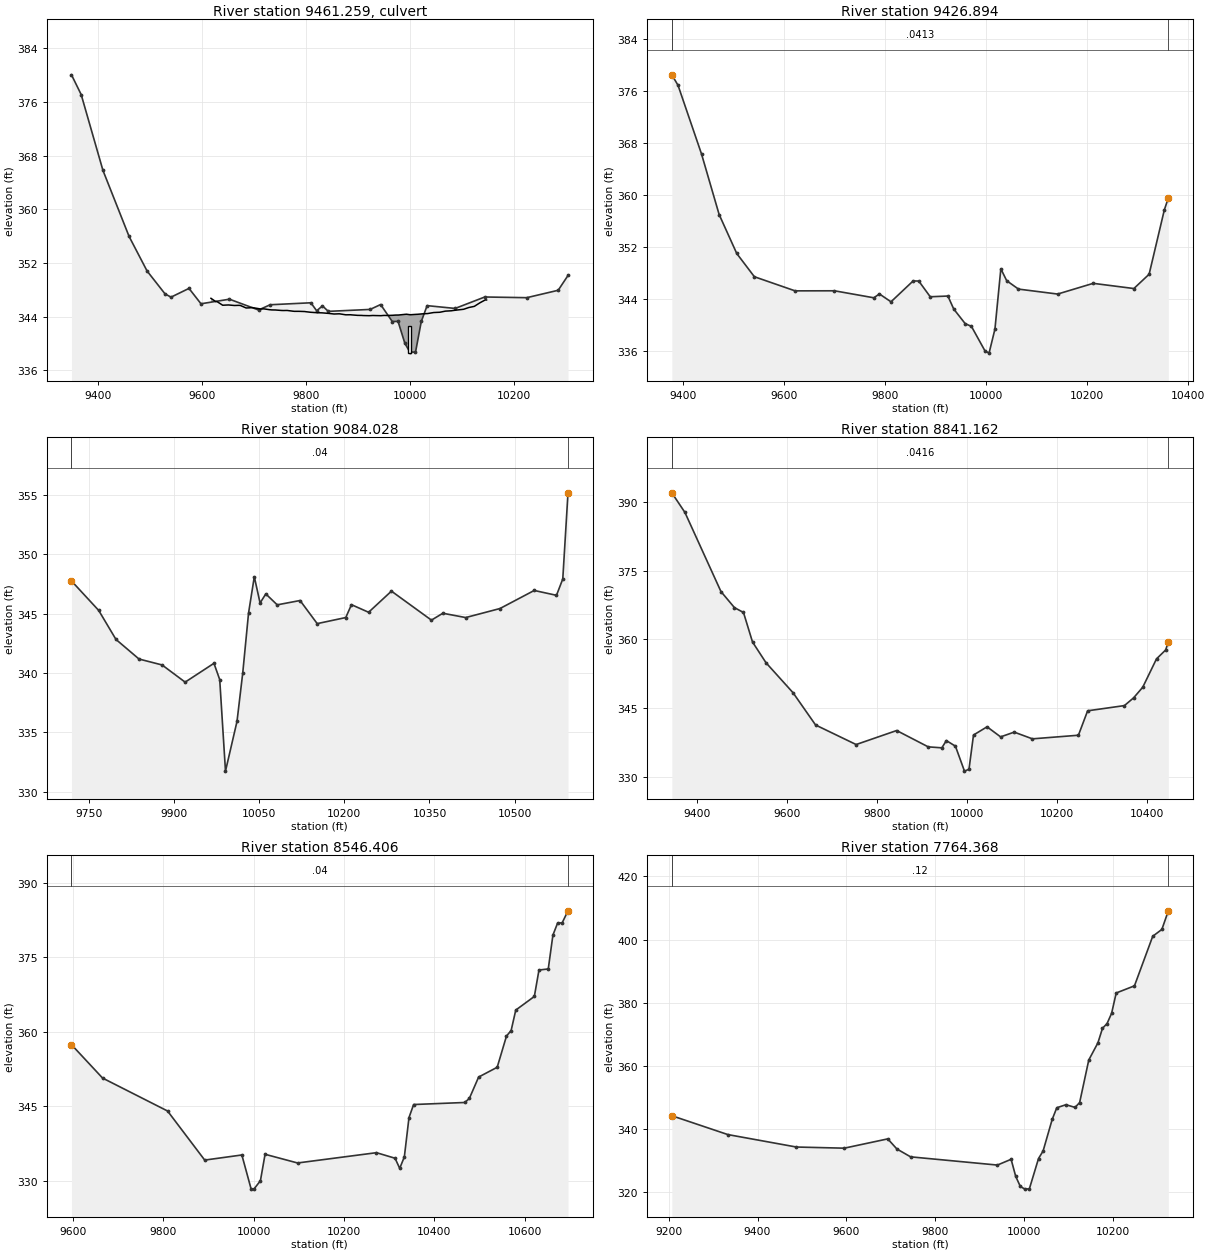
Type RM Length L Ch R = 2 ,9461.259,,,
Bridge Culvert--1,0,-1,-1, 0
Deck Dist Width WeirC Skew NumUp NumDn MinLoCord MaxHiCord MaxSubmerge Is_Ogee
18.613,19.27,2.6,0,74,74, , , 0.95, 0, 0,0,,
 9617.39 9626.76 9628.68 9639.96 9648.35 9651.24 9662.53 9669.94 9673.81 9685.10
 9691.52 9696.38 9707.66 9713.11 9718.95 9730.23 9734.70 9741.52 9752.80 9756.28
 9764.08 9775.37 9777.87 9786.65 9797.93 9799.45 9809.22 9820.50 9821.04 9831.79
 9842.63 9843.07 9854.35 9864.21 9865.64 9876.92 9885.80 9888.20 9899.49 9907.39
 9910.77 9922.06 9928.97 9933.34 9944.62 9950.56 9955.91 9967.19 9972.15 9978.48
 9989.76 9993.7310001.0410012.3310015.3210023.6110034.8910036.9010046.1810057.46
10058.4910068.7510080.0310080.0810084.2910092.7710103.3110103.9710113.8610124.40
10134.9410135.6010145.4810147.97
  346.74  346.24  346.27  345.71  345.74  345.75  345.67  345.69  345.68  345.30
  345.32  345.36  345.22  345.14  345.17  345.04  345.01  345.00  344.93  344.92
  344.93  344.82  344.80  344.80  344.77  344.75  344.66  344.60  344.60  344.57
  344.50  344.50  344.40  344.43  344.42  344.28  344.29  344.27  344.20  344.19
  344.17  344.15  344.18  344.17  344.15  344.19  344.18  344.21  344.24  344.25
  344.34  344.37  344.29  344.35  344.36  344.42  344.47  344.50  344.62  344.66
  344.67  344.83  344.88  344.88  344.93  345.01  345.10  345.11  345.37  345.54
  346.06  346.09  346.50  346.49
                                                                                
                                                                                
                                                                                
                                                                                
                                                                                
                                                                                
                                                                                
                                
 9617.39 9626.76 9628.68 9639.96 9648.35 9651.24 9662.53 9669.94 9673.81 9685.10
 9691.52 9696.38 9707.66 9713.11 9718.95 9730.23 9734.70 9741.52 9752.80 9756.28
 9764.08 9775.37 9777.87 9786.65 9797.93 9799.45 9809.22 9820.50 9821.04 9831.79
 9842.63 9843.07 9854.35 9864.21 9865.64 9876.92 9885.80 9888.20 9899.49 9907.39
 9910.77 9922.06 9928.97 9933.34 9944.62 9950.56 9955.91 9967.19 9972.15 9978.48
 9989.76 9993.7310001.0410012.3310015.3210023.6110034.8910036.9010046.1810057.46
10058.4910068.7510080.0310080.0810084.2910092.7710103.3110103.9710113.8610124.40
10134.9410135.6010145.4810147.97
  346.74  346.24  346.27  345.71  345.74  345.75  345.67  345.69  345.68  345.30
  345.32  345.36  345.22  345.14  345.17  345.04  345.01  345.00  344.93  344.92
  344.93  344.82  344.80  344.80  344.77  344.75  344.66  344.60  344.60  344.57
  344.50  344.50  344.40  344.43  344.42  344.28  344.29  344.27  344.20  344.19
  344.17  344.15  344.18  344.17  344.15  344.19  344.18  344.21  344.24  344.25
  344.34  344.37  344.29  344.35  344.36  344.42  344.47  344.50  344.62  344.66
  344.67  344.83  344.88  344.88  344.93  345.01  345.10  345.11  345.37  345.54
  346.06  346.09  346.50  346.49
                                                                                
                                                                                
                                                                                
                                                                                
                                                                                
                                                                                
                                                                                
                                
BR Coef=-1 , 0 , 0 ,, 0 ,,,0.8,-1,,0,
WSPro=,,,, 1 ,,,, 0 ,,,, 0 ,,,,-1 ,-1 ,-1 , 0 , 0 , 0 , 0 , 0
Culvert=2,4,5,19.27,0.013,0.4,1,8,1,338.57,10000,337.58,10000,Culvert #1, 0, 18.613
Culvert Bottom n=0.013
BC Design=,, 0 ,, 0 ,,,,,,

Type RM Length L Ch R = 1 ,9426.894,342.865800,342.865800,342.865800
XS GIS Cut Line= 5
476875.513680458748010.443817139476690.617847174747901.068817139
          476565747642.735446095476448.913117319747447.777304411
476197.177006215747421.735637754
#Sta/Elev= 30
9378.621 378.4469390.836376.84399437.311366.30159472.167357.00199507.023351.0166
9541.879347.44859622.432345.28049700.269345.29099778.106344.21749789.226344.8069
9812.098343.59999855.944 346.8069867.063346.78529889.704344.37419924.619344.4854
9936.258342.48379958.885340.24499971.173339.83189997.976336.067410006.09335.7208
10017.73339.426910029.37348.6675   10041346.835610064.28345.5505 10141.7  344.79
10212.07346.4337 10292.5345.637110322.66347.831310352.82357.732710360.68359.5393
#Mann= 3 , 0 , 0
9378.621  0.0413       09378.621  0.0413       010360.68  0.0413       0
#XS Ineff= 2 , 0
       09694.066        10033.54       0
Bank Sta=9378.621,10360.68
Exp/Cntr=0.3,0.1

Type RM Length L Ch R = 1 ,9084.028,242.866700,242.866700,242.866700
XS GIS Cut Line= 3
477072.177006185 747482.49952665476740.579783976747423.471748874
476205.857561767747362.707859963
#Sta/Elev= 30
9719.149347.74719767.067 345.2689797.539342.82199838.168  341.179878.796340.6716
9919.425339.22379970.211340.81019980.368339.43669990.526331.726410010.84335.9208
   10021340.023610031.15345.036110041.31348.103910051.47345.892210061.57346.6562
 10081.7345.735410121.96346.100810152.15344.153610202.48344.665710212.54345.7498
10242.73  345.1110282.99 346.89110353.44344.447210373.57345.027310413.83344.6647
10474.21345.4247 10534.6346.947510573.82346.538210584.92347.914810594.12355.1734
#Mann= 3 , 0 , 0
9719.149    0.04       09719.149    0.04       010594.12    0.04       0
#XS Ineff= 2 , 0
       09803.327        10067.49       0
Bank Sta=9719.149,10594.12
Exp/Cntr=0.3,0.1

Type RM Length L Ch R = 1 ,8841.162,294.755500,294.755500,294.755500
XS GIS Cut Line= 6
477294.080944061747286.570959806476928.352785438747274.890525326
476770.373856157747273.370884821476670.992735654747263.601516038
476497.232728094 747280.22651507476199.156016737747340.716754705
#Sta/Elev= 30
9344.828392.02429373.915387.73769453.932370.44969483.944366.93159503.959365.8768
9523.973359.43179553.995354.89149614.038 348.3379664.074341.2905 9754.11 337.018
9844.114340.07829914.258336.51089944.459336.29899954.527337.88259974.642336.6603
9994.713331.208310004.75331.618810014.77339.097410044.88340.8934   10075338.6934
 10105.2 339.73110145.59338.263510247.78339.052110268.22344.388610349.95  345.53
 10370.3347.217810390.65349.545410421.18355.738810441.53 357.68610447.48 359.437
#Mann= 3 , 0 , 0
9344.828  0.0416       09344.828  0.0416       010447.48  0.0416       0
#XS Ineff= 2 , 0
       09631.934        10029.28       0
Bank Sta=9344.828,10447.48
Exp/Cntr=0.3,0.1

Type RM Length L Ch R = 1 ,8546.406,782.038100,782.038100,782.038100
XS GIS Cut Line= 2
477151.945616543746961.881648824476082.501172125747215.353871047
#Sta/Elev= 30
9596.868357.36789665.668350.64329809.547344.00539891.763334.11469973.979335.1456
9994.533328.278310000.64328.264910015.09329.958210025.36335.2865 10097.3333.5346
10272.01335.608210313.12334.4881 10323.4332.446210333.68334.761210343.95342.6807
10354.23345.310910467.28345.722410477.55346.533810498.11350.847310539.22352.8196
10559.77359.106510570.05360.221410580.32364.340610621.43367.085710631.71372.4109
10652.26372.630110662.54379.446710672.82381.849210683.09 381.93210695.94384.3395
#Mann= 3 , 0 , 0
9596.868    0.04       09596.868    0.04       010695.94    0.04       0
#XS Ineff= 2 , 0
       09810.257        10126.61       0
Bank Sta=9596.868,10695.94
Exp/Cntr=0.3,0.1

Type RM Length L Ch R = 1 ,7764.368,308.434600,308.434600,308.434600
XS GIS Cut Line= 2
477127.640060991746725.770537689476040.834505439746982.714982152
#Sta/Elev= 30
9207.255344.26099333.276338.29269487.411334.35279595.076333.99119692.925336.9321
9713.476333.73279744.303331.24619939.541328.64429970.368330.47289980.644325.0913
9990.919321.920610001.19321.028610011.47321.136410032.02330.7129 10042.3333.0987
10062.85343.133710073.12346.790210093.68347.745110114.23346.8978 10124.5348.4306
10145.05361.898210165.61  367.3310175.88371.928610186.16373.427810196.43376.6848
10206.71383.108810247.81385.371210288.91401.061710309.47 403.23310324.02409.1142
#Mann= 3 , 0 , 0
9207.255    0.12       09207.255    0.12       010324.02    0.12       0
#XS Ineff= 2 , 0
       09832.939                       0
Bank Sta=9207.255,10324.02
Exp/Cntr=0.3,0.1

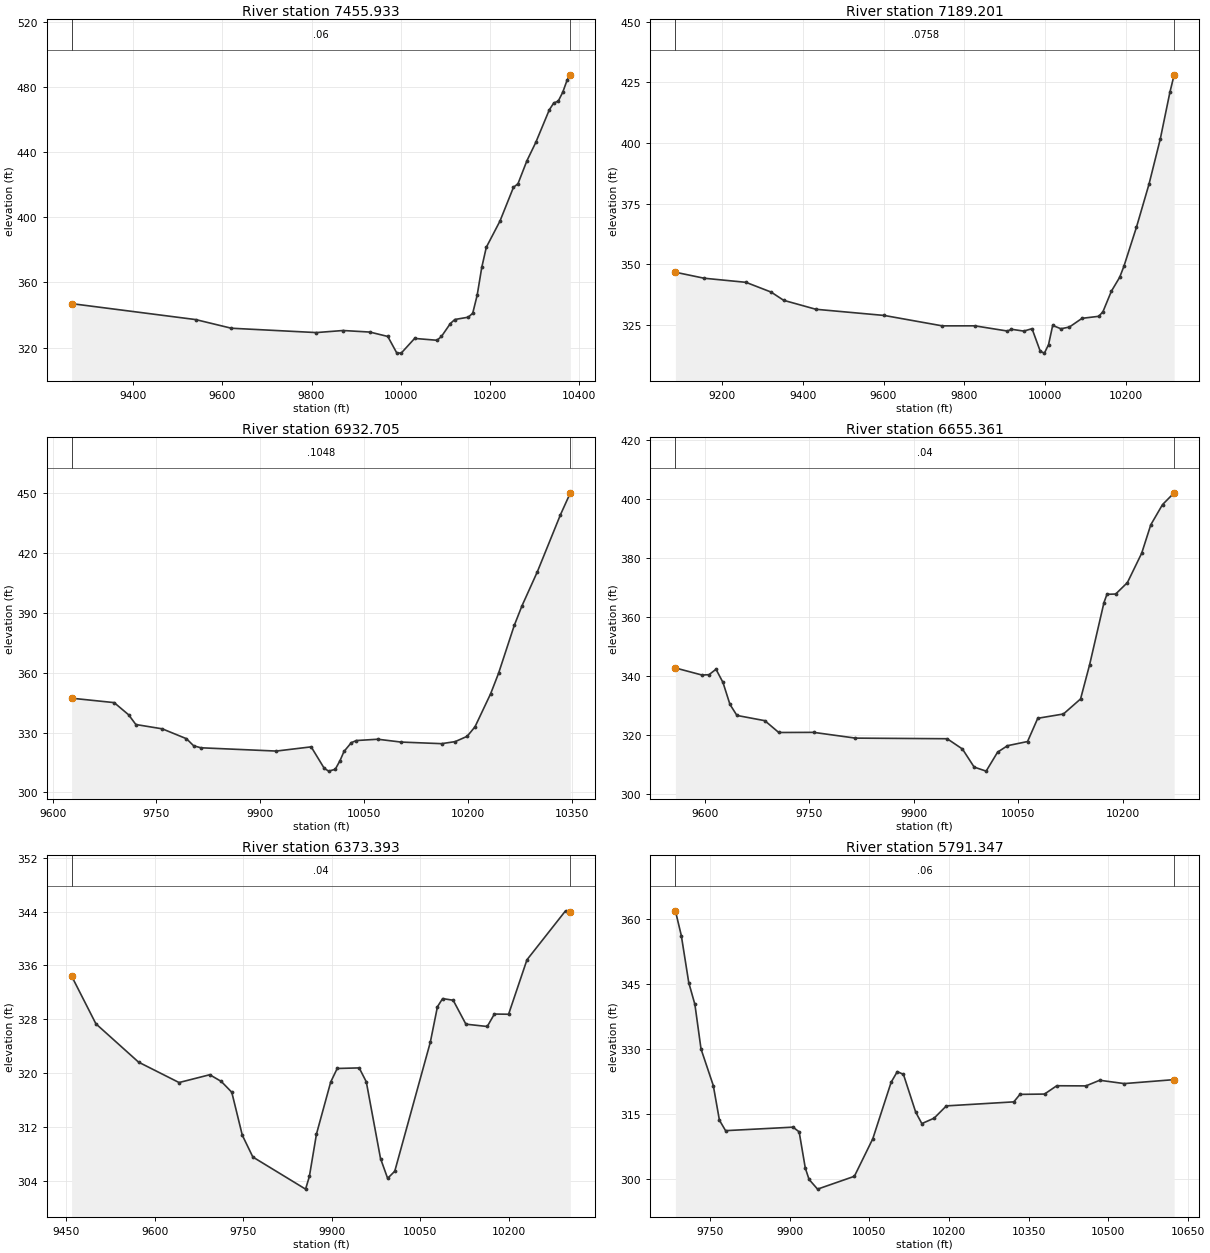
Type RM Length L Ch R = 1 ,7455.933,266.732200,266.732200,266.732200
XS GIS Cut Line= 4
477082.501172109746555.631648809476176.027519448746619.782228112
476110.714628501746633.079649255475967.917838766746645.909426585
#Sta/Elev= 30
9261.854347.0134 9540.05 337.225 9620.25331.90859810.725329.24149870.875330.5097
9931.025329.55059971.125326.85269991.175316.7425 10001.2316.623310031.28325.6512
 10081.4 324.51910091.43326.843310111.48334.8113 10121.5337.269410151.58338.6913
 10161.6341.115610171.64352.252210181.85369.217410192.05381.607710222.67397.6722
10253.03418.442710263.07420.600110283.15434.732510303.23446.095710333.35 465.991
10343.39470.217110353.43471.340310363.47476.764110373.51484.379610380.62 487.495
#Mann= 3 , 0 , 0
9261.854    0.06       09261.854    0.06       010380.62    0.06       0
#XS Ineff= 2 , 0
       09914.209                       0
Bank Sta=9261.854,10380.62
Exp/Cntr=0.3,0.1

Type RM Length L Ch R = 1 ,7189.201,256.496500,256.496500,256.496500
XS GIS Cut Line= 6
477143.265060991746479.242759913476559.499327272746315.000000015
476328.160894334746343.826093286476208.200204641746369.980995208
476180.117063701 746379.53291215475944.890751958 746444.09279196
#Sta/Elev= 30
9084.264346.79889155.179344.33489259.062342.63849321.466338.61889352.556335.2268
9432.235331.53689601.874 328.9839745.615324.69649826.234324.71029906.853322.5662
 9916.93323.28619947.527322.54459967.997323.53239988.467314.19239998.702313.4613
10008.94316.978910019.17324.866110039.64323.502810060.58324.215310091.95327.8041
10133.43328.635810143.79330.555710164.53338.950810185.27344.745710195.64349.2393
10226.75365.349210257.86383.094310285.84401.732410309.71421.017810320.19428.1497
#Mann= 3 , 0 , 0
9084.264  0.0758       09084.264  0.0758       010320.19  0.0758       0
#XS Ineff= 2 , 0
       0 9851.24                       0
Bank Sta=9084.264,10320.19
Exp/Cntr=0.3,0.1

Type RM Length L Ch R = 1 ,6932.705,277.343300,277.343300,277.343300
XS GIS Cut Line= 6
476533.890060991745997.471926585476281.285894334746072.992759913
476187.563721418746110.995788038476091.521430552746178.724211276
476014.696272194746223.953286678475882.205467075746291.484280646
#Sta/Elev= 30
9627.433347.22779688.899345.01429709.774338.91489720.211334.04129758.448331.8715
9793.272326.9338 9803.71323.37819814.147322.38399923.039320.73819973.404322.8485
9992.219312.11829998.675310.685510008.16311.600910015.01315.909910020.81320.5395
10031.34324.941110038.79326.019610069.69326.664910103.07325.248210161.62324.4482
10181.33 325.46410198.62328.125410209.97332.880610232.66 349.53510244.01359.7144
10266.66383.670210277.79393.477510300.06410.599310333.46439.204210347.71450.1329
#Mann= 3 , 0 , 0
9627.433  0.1048       09627.433  0.1048       010347.71  0.1048       0
#XS Ineff= 2 , 0
       09926.174                       0
Bank Sta=9627.433,10347.71
Exp/Cntr=0.3,0.1

Type RM Length L Ch R = 1 ,6655.361,281.968600,281.968600,281.968600
XS GIS Cut Line= 6
476413.230338752 745894.17331548476040.834505439 745901.98581548
475978.403339535745930.095796466475942.139639109745966.008507729
475893.566074044746011.545119271475767.574968725746104.960658759
#Sta/Elev= 30
9558.055 342.8299596.293340.42839606.296340.55549616.298342.3919  9626.3337.9185
9636.302330.49269646.304326.75269686.313324.97829706.318 320.9779756.329321.0208
9816.342319.07129947.898318.86439969.832315.37049986.588 309.25710003.79307.8946
10020.18314.312710034.39316.504210063.18  317.9210077.81325.790310114.65327.2448
10139.21332.336610152.18343.907710172.79364.979710177.08367.777310189.58367.8626
10206.37371.731410226.87381.678510239.95391.317410256.74398.144810273.46402.1344
#Mann= 3 , 0 , 0
9558.055    0.04       09558.055    0.04       010273.46    0.04       0
#XS Ineff= 2 , 0
       09902.563                       0
Bank Sta=9558.055,10273.46
Exp/Cntr=0.3,0.1

Type RM Length L Ch R = 1 ,6373.393,582.045700,582.045700,582.045700
XS GIS Cut Line= 2
476259.150477678745403.070884928475558.195616543745876.161162704
#Sta/Elev= 30
9459.159334.4211 9500.36327.33479572.747321.63959641.362318.61239693.392319.7717
9712.863318.78229730.738317.17349748.614310.78389766.489307.55289855.866302.7852
9862.295304.6628 9874.36310.97289898.489  318.699909.492320.70149946.747320.7855
9958.811 318.725 9982.94 307.3339995.005304.388410007.07305.441310067.39324.6029
10079.46329.873610088.25331.078310106.12330.833110127.71  327.2810163.91326.9342
10175.97328.7822 10200.1328.755110231.25336.841510296.62  344.1110304.83343.9935
#Mann= 3 , 0 , 0
9459.159    0.04       09459.159    0.04       010304.83    0.04       0
#XS Ineff= 2 , 0
       09934.905                       0
Bank Sta=9459.159,10304.83
Exp/Cntr=0.3,0.1

Type RM Length L Ch R = 1 ,5791.347,800.119700,800.119700,800.119700
XS GIS Cut Line= 2
475886.787552029745009.452787057475073.600696758745477.890522452
#Sta/Elev= 30
9685.182361.78789696.295356.09659710.325345.24079721.866340.21799733.407329.9447
9756.488321.52369768.028313.54399779.569311.13079906.514311.93789918.055310.8497
9929.595 302.5089936.701299.88899952.676297.656710021.92300.612710056.54309.2473
10091.16322.2991 10102.7324.738510114.24324.097610137.32315.403810148.87312.7565
10171.95314.007610195.03 316.83810321.97317.766310333.51 319.49310379.68 319.563
10402.76  321.4810457.58321.443710483.54 322.742 10529.7321.977510623.64 322.891
#Mann= 3 , 0 , 0
9685.182    0.06       09685.182    0.06       010623.64    0.06       0
#XS Ineff= 2 , 0
       0                10108.17       0
Bank Sta=9685.182,10623.64
Exp/Cntr=0.3,0.1

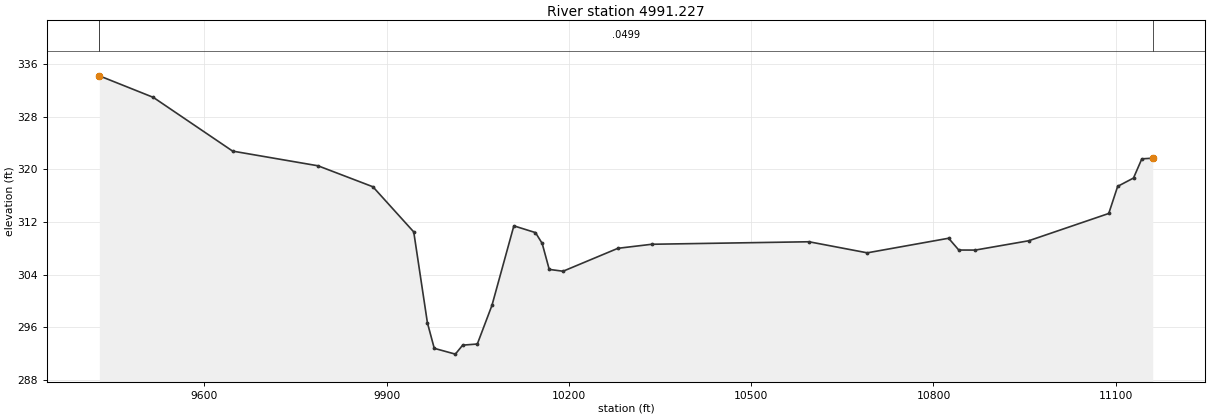
Type RM Length L Ch R = 1 ,4991.227,0.000000,0.000000,0.000000
XS GIS Cut Line= 6
 475893.51529935 744341.77148807475442.126410484 744380.83398807
475196.218448013744525.896452561475037.881159782744607.356704712
474903.931966037744719.375654727474465.563910514745188.125654712
#Sta/Elev= 30
9427.392334.22539516.238330.95089646.724 322.7889787.247320.55569877.583317.3687
9944.774310.50799967.287296.68969978.544292.821410013.24291.941610025.29293.3063
 10049.4293.4784 10073.5299.356610109.51 311.43110145.11310.403710156.11308.7632
10167.73304.8132 10190.5304.537210280.73308.0188 10336.5308.633810595.22309.0139
10691.06307.331710824.94309.547910841.66307.758310868.86307.750310956.71309.1647
11088.47313.312211103.11  317.4311129.18318.695211142.88321.612411160.85321.7113
#Mann= 3 , 0 , 0
9427.392  0.0499       09427.392  0.0499       011160.85  0.0499       0
#XS Ineff= 2 , 0
       09905.504         10113.2       0
Bank Sta=9427.392,11160.85
Exp/Cntr=0.3,0.1